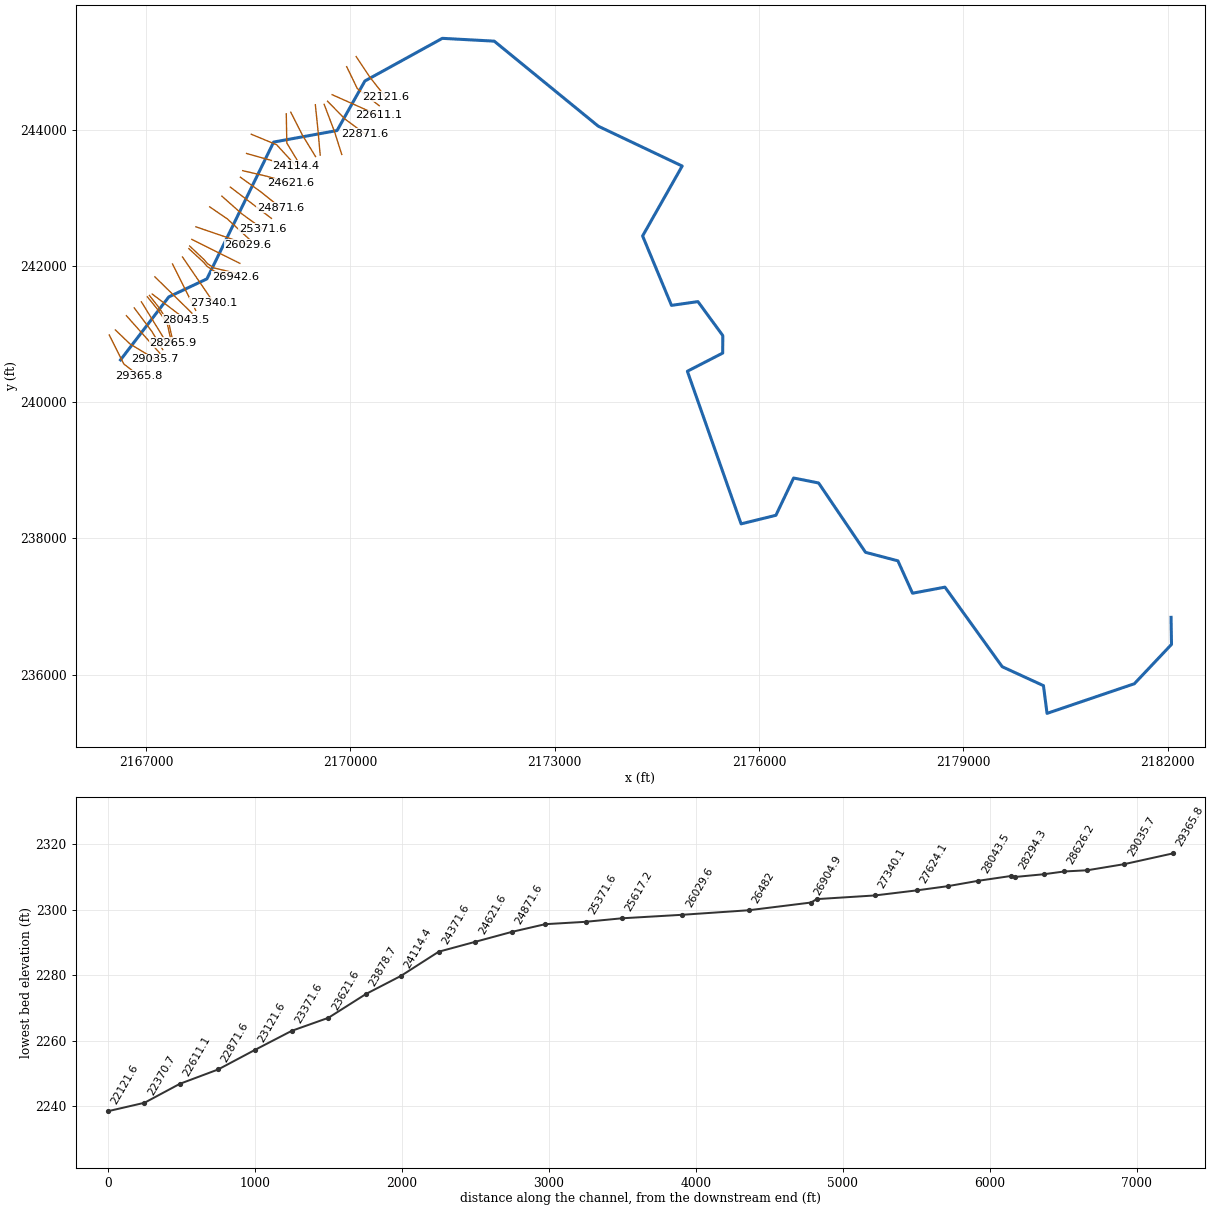
--- COVECK.prj (project) ---

Proj Title=COVECK
Current Plan=p01
Default Exp/Contr=0,0
English Units
Geom File=g01
Flow File=f01
Plan File=p01
BEGIN DESCRIPTION:
END DESCRIPTION:
DSS Export Rating Curves= 0
DSS Export Rating Curve Sorted= 0
DSS Export Volume Flow Curves= 0
DXF OffsetX= 0
DXF OffsetY= 0
DXF ScaleX= 0
DXF ScaleY= 0

--- COVECK.p01 (plan) ---

Plan Title=Floodplain
Program Version=4.00
Geom File=g01
Flow File=f01
K Sum by GR=0
Std Step Tol=0.01
Critical Tol=0.01
Num of Std Step Trials=20
Max Error Tol=0.3
Flow Tol Ratio=0.001
Split Flow NTrial=30
Split Flow Tol=0.02
Split Flow Ratio=0.02
Log Output Level=0
Friction Slope Method=1
Unsteady Friction Slope Method=2
Unsteady Bridges Friction Slope Method=1
Global Log Level=0
CheckData=False
Run HTab=0
Run UNet=0
Run PostProcess=0
UNET Theta=0
UNET Theta Warmup=0
UNET ZTol=0
UNET ZSATol=0
UNET MxIter=0
UNET MaxInSteps=0
UNET DtIC=0
UNET DtMin=0
UNET MaxCRTS=0
UNET WFStab=0
UNET SFStab=0
UNET WFX=0
UNET SFX=0
UNET DSS MLevel=0
UNET DZMax Abort=0
UNET Convert EG Bridges=0
UNET Use Existing IB Tables=0
UNET Froude Limit=0
UNET Froude Power=0
Write IC File=0
Echo Input=False
Echo Output=False
Write Detailed=0

--- COVECK.f01 (steady flow) ---

Flow Title=NFF Regression Equation
Program Version=4.10
Number of Profiles= 1
Profile Names=P100yr
River Rch & RM=COVECK,Main            ,29365.8
635.9457
River Rch & RM=COVECK,Main            ,27834
697.1564
River Rch & RM=COVECK,Main            ,27340.1
775.1405
River Rch & RM=COVECK,Main            ,26029.6
835.9762
River Rch & RM=COVECK,Main            ,24871.6
 874.511
River Rch & RM=COVECK,Main            ,24371.6
1031.076
River Rch & RM=COVECK,Main            ,22611.1
1063.728
River Rch & RM=COVECK,Main            ,20871.6
1174.336
River Rch & RM=COVECK,Main            ,20371.6
1292.259
River Rch & RM=COVECK,Main            ,19871.6
 1707.92
River Rch & RM=COVECK,Main            ,15366.5
1832.454
River Rch & RM=COVECK,Main            ,9871.8
2025.727
River Rch & RM=COVECK,Main            ,2680.4
3266.245
River Rch & RM=COVECK,Main            ,100.4
 3364.86
Boundary for River Rch & Prof#=COVECK,Main            , 1
Up Type= 0
Dn Type= 3
Dn Slope=0.0077
DSS Import GetInterval= 0
DSS Import GetPeak= 0
DSS Import FillOption= 0

--- COVECK.g01 (geometry) ---

Geom Title=USGS 1m DEM
Program Version=4.10

River Reach=COVECK          ,Main
Reach XY= 30
     2166623.512      240619.327     2167332.063      241543.806
     2167891.958      241808.563     2168871.776      243815.941
     2169802.766      243985.212     2170211.837      244712.208
      2171348.99      245338.294     2172110.708      245297.061
     2173639.277      244048.762     2174871.048      243464.126
     2174289.885      242438.302     2174714.147      241419.421
     2175102.602       241474.76     2175467.185      240976.713
       2175466.1      240719.552     2174947.437      240452.625
     2175736.283      238213.041      2176247.35       238338.91
     2176507.767      238885.784     2176874.521      238813.085
     2177563.539       237795.29       2178038.8      237670.507
     2178253.644      237195.246     2178729.989      237284.222
     2179570.918      236116.687     2180176.387      235838.909
     2180229.083      235431.968      2181510.89      235866.738
      2182056.68      236443.995      2182050.17       236841.13

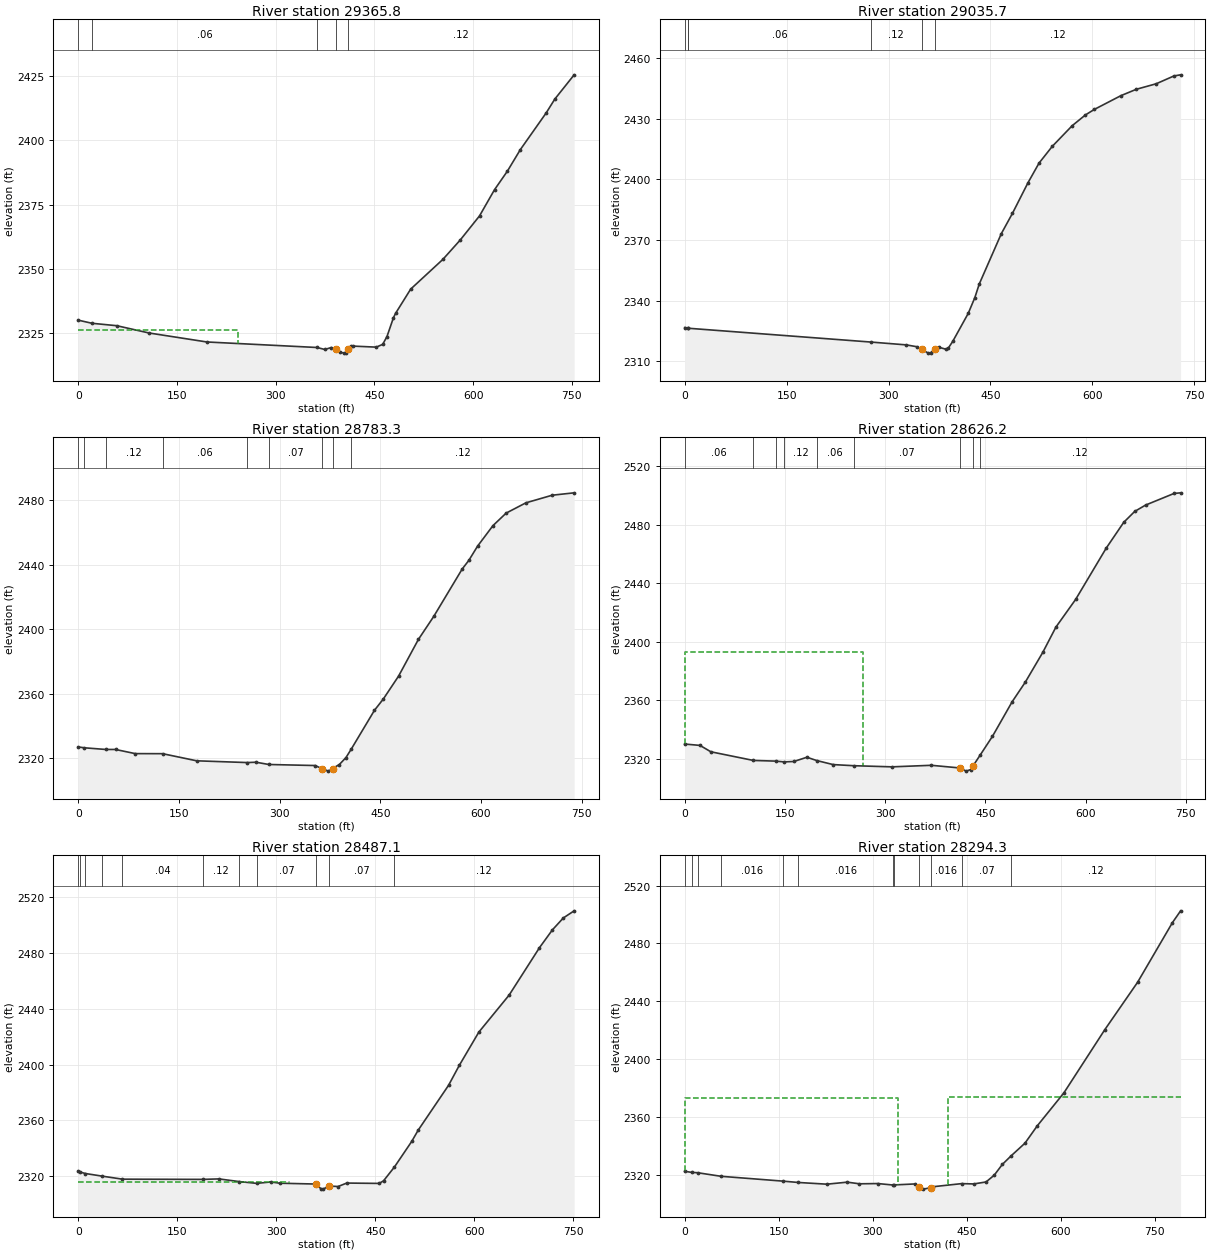
Type RM Length L Ch R = 1 ,29365.8 ,290.6,330.1,366.4
XS GIS Cut Line= 3
     2166457.782      240984.502     2166671.219      240559.321
     2166891.433      240389.926
#Sta/Elev= 30
       0  2330.1   20.952328.882    58.6 2327.94   107.5 2325.11   195.5 2321.61
  362.842319.461   374.7 2318.69   384.5 2319.45     391 2318.87   397.5 2317.66
   404.1 2317.27   407.3 2317.44   410.6 2318.81   413.8 2319.86   417.1 2320.01
   452.9  2319.6   462.7 2320.69   469.2 2323.73     479 2331.04   482.3 2332.77
   505.2 2342.18   554.2 2353.76   580.3 2361.22   609.8 2370.66   632.6 2380.86
   652.2 2388.09   671.9 2396.48   711.1 2410.73   724.2 2416.11   753.6 2425.55
#Mann= 5 ,-1 , 0
       0     .08       0   20.95     .06       0  362.84     .12       0
     391    .045       0   410.6     .12       0
#XS Ineff= 2 , 0
          242.23  2326.1
Permanent Ineff=
       F       F
Bank Sta=391,410.6
XS Rating Curve= 0 ,0
Exp/Cntr=0.3,0.1

Type RM Length L Ch R = 1 ,29035.7 ,258.7,252.4,230.1
XS GIS Cut Line= 3
     2166547.561      241059.036     2166759.305      240855.762
     2167131.973      240628.773
#Sta/Elev= 30
       0 2326.63    4.372326.373    5.612326.296   274.1 2319.47   326.1 2318.07
   342.4 2317.12   348.8 2315.85   358.6 2313.99   361.9 2314.13   368.4 2316.27
   374.9 2316.82   384.7  2315.9     388 2316.48   394.5 2319.79   417.3 2333.65
     427 2341.42   433.6 2348.24   466.1 2373.17   482.4 2383.17   505.2 2398.27
   521.5 2408.02     541 2416.32   570.3 2426.54   589.8 2431.87   602.9  2434.6
     642 2441.41   664.8 2444.57   694.1 2447.31   720.1 2451.17   729.9 2451.72
#Mann= 6 ,-1 , 0
       0    .016       0    4.37     .12       0    5.61     .06       0
   274.1     .12       0   348.8    .045       0   368.4     .12       0
Bank Sta=348.8,368.4
XS Rating Curve= 0 ,0
Exp/Cntr=0.3,0.1

Type RM Length L Ch R = 1 ,28783.3 ,147.2,157.1,149.6
XS GIS Cut Line= 2
     2166709.129      241268.413     2167200.728      240716.994
#Sta/Elev= 30
       0  2327.1    9.172326.582   40.822325.552    55.6 2325.54      85 2322.97
  125.65 2322.93   176.5 2318.51  251.532317.424   264.8 2317.63  283.922316.228
     353 2315.58   363.8  2313.5   372.6 2312.11   378.8 2313.73     389 2316.22
   398.8 2320.51  406.912325.917   441.3 2349.87   454.4 2356.81   477.2 2371.06
   506.7  2393.8   529.5 2408.03     572 2437.52   581.8 2442.82   594.9  2451.7
   617.8 2464.41   637.4 2472.16   666.8 2478.53     706 2483.26   738.7 2484.74
#Mann= 9 ,-1 , 0
       0     .12       0    9.17     .06       0   40.82     .12       0
  125.65     .06       0  251.53     .12       0  283.92     .07       0
   363.8    .045       0   378.8     .07       0  406.91     .12       0
Bank Sta=363.8,378.8
XS Rating Curve= 0 ,0
Exp/Cntr=0.3,0.1

Type RM Length L Ch R = 1 ,28626.2 ,142,139.1,114.1
XS GIS Cut Line= 3
     2166824.426      241382.359     2167084.843      241034.703
     2167242.395       240770.38
#Sta/Elev= 30
       0 2330.23    22.9  2329.3    39.2 2324.94  102.752319.038  136.122318.572
  148.832318.052   163.3 2318.32   182.9 2321.21  197.572318.967   222.1 2316.21
  253.012315.441   310.3 2314.66   369.1 2315.72   411.5 2313.91   421.3 2311.74
   427.8 2312.78   431.1 2315.04  441.782322.426   460.6 2335.53     490 2359.08
   509.7 2372.49   535.9 2392.84   555.5 2410.06     585 2428.94   630.8 2463.99
     657 2481.59   673.4 2489.02   689.7 2493.36   732.3  2501.3   742.1 2501.72
#Mann= 9 ,-1 , 0
       0     .06       0  102.75     .12       0  136.12     .04       0
  148.83     .12       0  197.57     .06       0  253.01     .07       0
   411.5    .045       0   431.1     .07       0  441.78     .12       0
#XS Ineff= 2 , 0
          266.33 2392.79
Permanent Ineff=
       F       F
Bank Sta=411.5,431.1
XS Rating Curve= 0 ,0
Exp/Cntr=0.3,0.1

Type RM Length L Ch R = 1 ,28487.1 ,158.9,192.8,173.8
XS GIS Cut Line= 2
     2166929.895      241470.901     2167324.426      240831.578
#Sta/Elev= 30
       0  2323.6    2.382323.182   10.772322.063   35.762320.217   67.022318.013
     1892317.858   213.2  2318.2     2442316.272  270.392315.012     292 2316.03
   305.1 2315.12   360.9 2314.52   367.4 2311.22   370.7 2310.89   380.6 2313.07
   393.7 2312.76   406.8 2315.23     456 2314.97   462.6 2316.87  478.872326.599
   505.2 2344.98     515 2353.03     561  2385.1   577.4 2399.47   606.9 2423.16
   652.8 2449.64   698.8 2483.57   718.4  2496.3   734.9  2504.8   751.3  2509.9
#Mann= 11 ,-1 , 0
       0     .06       0    2.38     .12       0   10.77     .06       0
   35.76     .12       0   67.02     .04       0     189     .12       0
     244     .06       0  270.39     .07       0   360.9    .045       0
   380.6     .07       0  478.87     .12       0
#XS Ineff= 2 , 0
          319.25 2315.94
Permanent Ineff=
       F       F
Bank Sta=360.9,380.6
XS Rating Curve= 0 ,0
Exp/Cntr=0.3,0.1

Type RM Length L Ch R = 1 ,28294.3 ,113.1,28.4,27.2
XS GIS Cut Line= 4
     2167017.135      241545.119     2167160.364      241369.338
     2167307.499      241158.401     2167375.208      240858.922
#Sta/Elev= 30
       0 2322.41   11.122321.657   20.682321.409   57.882318.947  156.242315.617
  181.332314.669   226.8 2313.49   259.3 2314.89   278.8 2313.75   308.1 2313.92
  331.822312.927  334.372312.987   366.7 2313.64   373.2 2311.58   379.8 2310.07
   392.8 2310.98     396 2311.72  441.79 2313.88   461.1 2313.66   480.7 2315.03
   493.7 2319.71   506.8 2327.23  521.072333.249   542.7 2341.82   562.3  2353.8
   604.8 2376.61   670.1 2420.33   722.4 2453.11   777.9 2494.32     791  2502.5
#Mann= 12 ,-1 , 0
       0     .06       0   11.12    .016       0   20.68     .12       0
   57.88    .016       0  156.24     .12       0  181.33    .016       0
  331.82     .07       0  334.37    .016       0   373.2    .045       0
   392.8    .016       0  441.79     .07       0  521.07     .12       0
#XS Ineff= 2 , 0
          339.97 2373.02  419.67         2373.98
Permanent Ineff=
       F       F
Bank Sta=373.2,392.8
XS Rating Curve= 0 ,0
Exp/Cntr=0.3,0.1

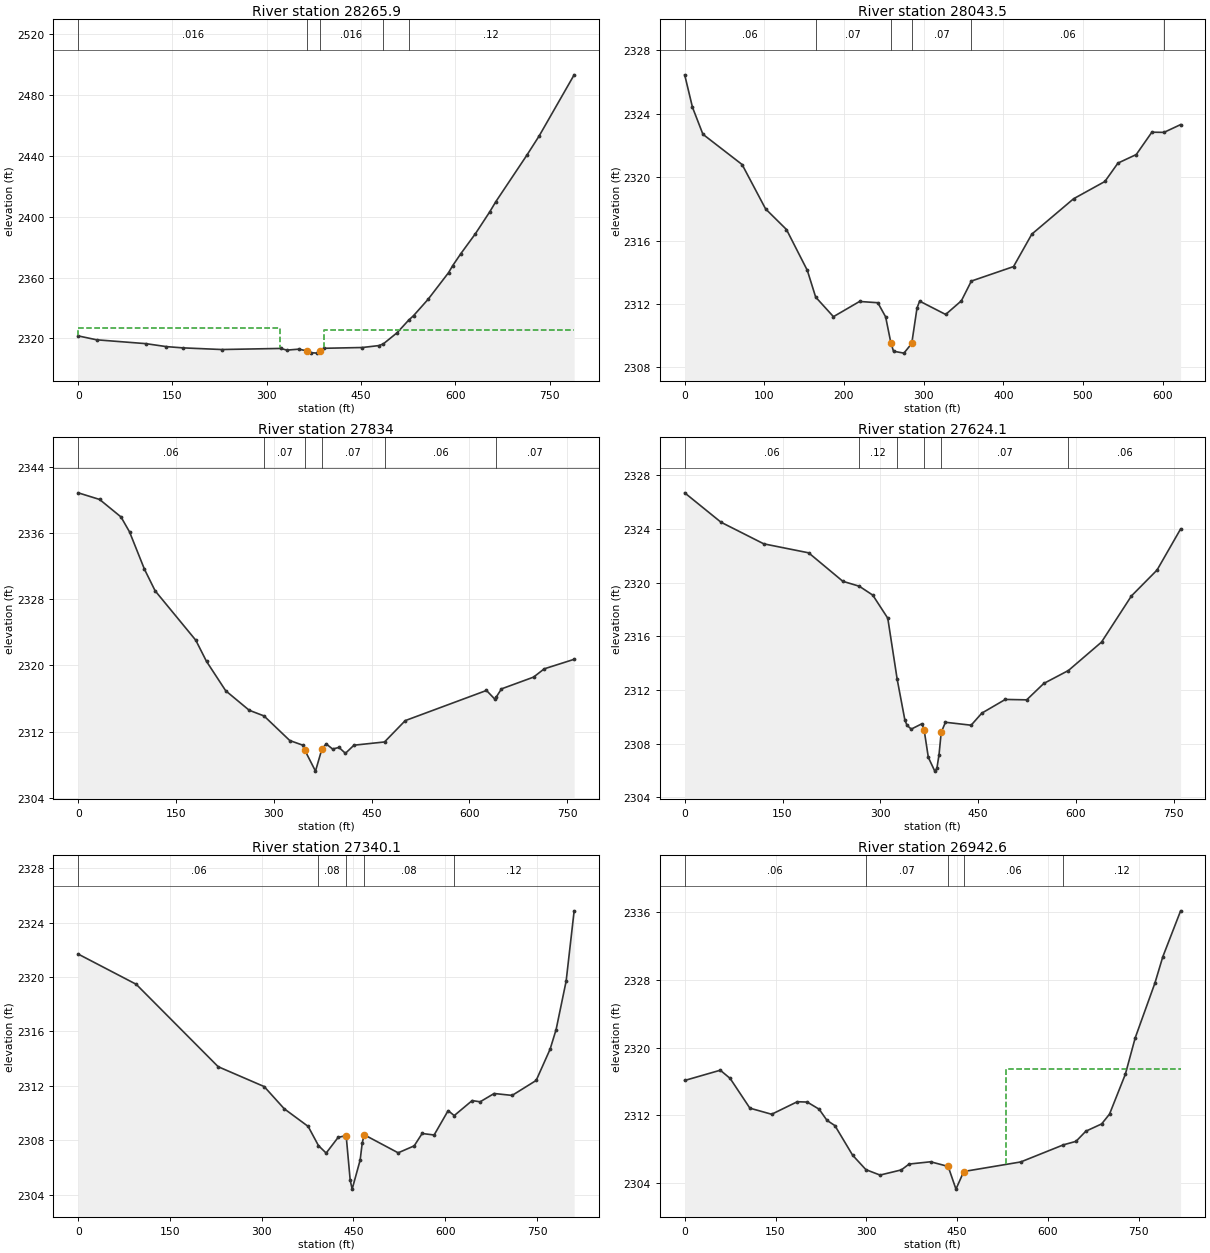
Type RM Length L Ch R = 1 ,28265.9 ,120.4,222.4,234.9
XS GIS Cut Line= 4
     2167048.385      241564.651     2167185.103      241390.172
     2167330.937      241167.515     2167396.041      240873.244
#Sta/Elev= 30
       0 2321.68    29.3 2319.12   107.6  2316.6   140.2 2314.65   166.2 2313.83
   228.2 2312.74   322.3 2313.45     332 2312.35   351.5 2312.99   364.5 2311.72
     371 2310.63   380.7 2310.37     384 2311.52   390.4 2313.54   452.1 2314.06
   478.1 2315.31  485.332316.375   507.5 2323.78   525.62331.922   533.7 2335.01
   556.6 2345.63   589.4 2363.25   595.9 2367.81     609 2375.77     632 2388.76
   654.9 2403.18   664.7 2409.93   713.9 2440.34   733.5    2453   789.2 2493.14
#Mann= 5 ,-1 , 0
       0    .016       0   364.5    .045       0     384    .016       0
  485.33     .07       0   525.6     .12       0
#XS Ineff= 2 , 0
           321.9 2326.82  391.86         2325.49
Permanent Ineff=
       F       F
Bank Sta=364.5,384
XS Rating Curve= 0 ,0
Exp/Cntr=0.3,0.1

Type RM Length L Ch R = 1 ,28043.5 ,200.6,209.5,204.3
XS GIS Cut Line= 2
     2167088.749      241585.484     2167584.843      241209.182
#Sta/Elev= 30
       0 2326.46     9.8 2324.41    22.9 2322.71    72.1  2320.8   101.6    2318
   127.8  2316.7     154 2314.12  164.472312.435   186.8  2311.2   219.6 2312.16
   242.5 2312.08   252.3 2311.19   258.9 2309.55   262.2 2309.02   275.3  2308.9
   285.1 2309.51   291.7 2311.74     295 2312.18   327.7 2311.34   347.4  2312.2
  359.952313.447   412.9 2314.36   435.9 2316.41   488.3 2318.64   527.6 2319.73
     544 2320.89     567 2321.43   586.6 2322.84  601.832322.829   622.7 2323.32
#Mann= 6 ,-1 , 0
       0     .06       0  164.47     .07       0   258.9    .045       0
   285.1     .07       0  359.95     .06       0  601.83     .12       0
Bank Sta=258.9,285.1
XS Rating Curve= 0 ,0
Exp/Cntr=0.3,0.1

Type RM Length L Ch R = 1 ,27834   ,223.9,209.9,193.9
XS GIS Cut Line= 2
     2167128.145      241837.969     2167671.849      241305.844
#Sta/Elev= 30
       0 2340.84    32.8 2340.04    65.6 2337.93    78.7 2336.13   101.6 2331.62
     118 2329.01   180.4 2323.04   196.8 2320.49   226.3 2316.94   262.3 2314.59
  285.022313.904   324.6 2310.93   344.3 2310.38   347.6 2309.77     364 2307.24
   373.8  2309.9   380.4 2310.53   390.2 2309.91   400.1  2310.1   409.9 2309.39
     423 2310.37  469.892310.762   501.7 2313.34   626.3 2316.98   639.4 2315.91
  641.242316.177   649.3 2317.17   698.5 2318.59   714.9 2319.59   760.8 2320.74
#Mann= 6 ,-1 , 0
       0     .06       0  285.02     .07       0   347.6    .045       0
   373.8     .07       0  469.89     .06       0  641.24     .07       0
Bank Sta=347.6,373.8
XS Rating Curve= 0 ,0
Exp/Cntr=0.3,0.1

Type RM Length L Ch R = 1 ,27624.1 ,276.1,284,285.4
XS GIS Cut Line= 2
     2167386.926       242026.89     2167727.045       241346.82
#Sta/Elev= 30
       0 2326.69    55.7  2324.5   121.3 2322.89   190.1 2322.22   242.5  2320.1
  267.742319.732   288.4 2319.07   311.4 2317.35  325.842312.795   337.6 2309.77
   340.9 2309.37   347.4 2309.09   363.8 2309.49   367.1 2309.04   373.6 2306.98
   383.5 2305.96   386.7 2306.16     390 2307.19   393.3 2308.84   399.8  2309.6
   439.2 2309.38   455.6 2310.28   491.6  2311.3   524.4 2311.27   550.6 2312.49
  588.362313.455   639.1 2315.57     685 2319.01   724.3 2320.94   760.4    2324
#Mann= 6 ,-1 , 0
       0     .06       0  267.74     .12       0  325.84     .07       0
   367.1    .045       0   393.3     .07       0  588.36     .06       0
Bank Sta=367.1,393.3
XS Rating Curve= 0 ,0
Exp/Cntr=0.3,0.1

Type RM Length L Ch R = 1 ,27340.1 ,395.6,397.5,395.2
XS GIS Cut Line= 2
      2167532.76      242129.755     2167990.367      241460.585
#Sta/Elev= 30
       0 2321.69    94.8 2319.47   228.8 2313.41     304 2311.95   336.7 2310.32
   375.9 2309.02  392.682307.613   405.3 2307.06     425 2308.22     438 2308.34
   444.6 2305.07   447.8 2304.41   460.9 2306.55   464.2 2307.78   467.4 2308.41
     523 2307.08   549.2 2307.59   562.2  2308.5   581.8 2308.39   604.7 2310.18
  614.692309.817     644 2310.92     657 2310.83   679.9 2311.44   709.3  2311.3
   748.6  2312.4   771.4  2314.7   781.2 2316.14   797.6  2319.7   810.7 2324.87
#Mann= 5 ,-1 , 0
       0     .06       0  392.68     .08       0     438    .045       0
   467.4     .08       0  614.69     .12       0
Bank Sta=438,467.4
XS Rating Curve= 0 ,0
Exp/Cntr=0.3,0.1

Type RM Length L Ch R = 1 ,26942.6 ,48.1,37.6,46.4
XS GIS Cut Line= 5
     2167626.307        242252.1     2167844.623      242050.711
     2167891.932      241994.288     2168001.307      241920.069
     2168307.297      241840.642
#Sta/Elev= 30
       0 2316.11    58.8 2317.32    75.1 2316.35   107.7 2312.84   143.6 2312.12
     186  2313.6   202.4 2313.56     222 2312.72     235  2311.4   248.1 2310.78
   277.4 2307.28   299.32305.579   322.6 2304.94   357.8 2305.55   370.6 2306.24
   406.1 2306.51   435.1 2305.96     448 2303.28   460.9 2305.36     555 2306.49
  625.542308.512   646.2 2308.92   662.5 2310.12   688.6 2310.98   701.6 2312.14
   727.7 2316.84     744 2321.14   776.6 2327.62   789.6 2330.72     819 2336.14
#Mann= 5 ,-1 , 0
       0     .06       0   299.3     .07       0   435.1    .045       0
   460.9     .06       0  625.54     .12       0
#XS Ineff= 2 , 0
                           530.9          2317.5
Permanent Ineff=
       F       F
Bank Sta=435.1,460.9
XS Rating Curve= 0 ,0
Exp/Cntr=0.3,0.1

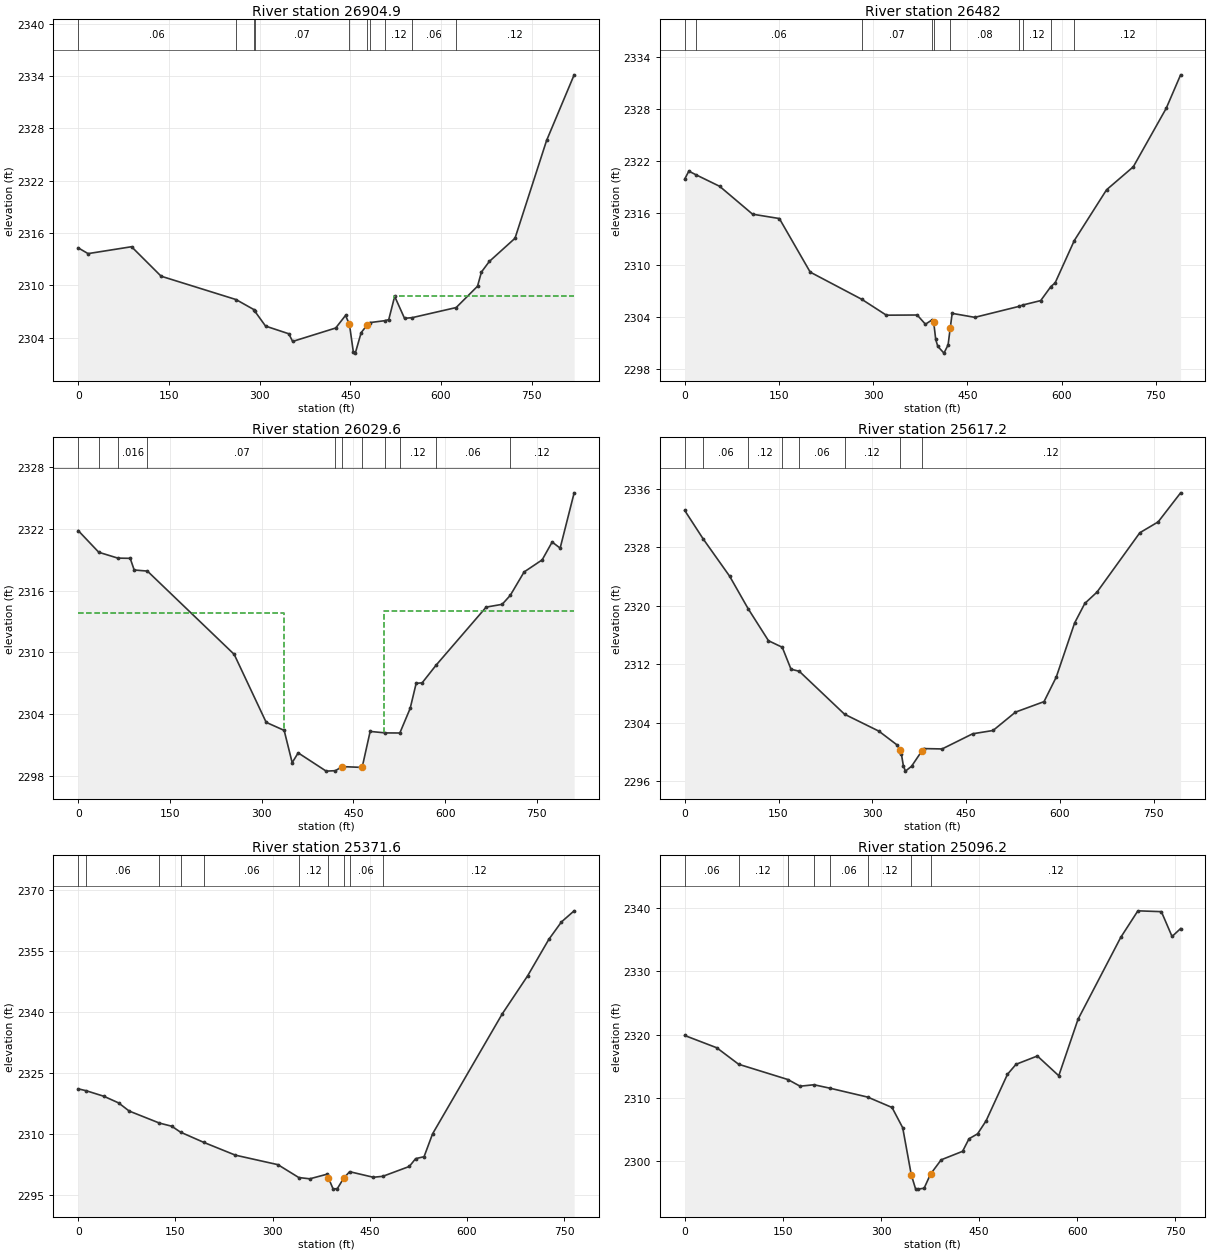
Type RM Length L Ch R = 1 ,26904.9 ,257,423,398.1
XS GIS Cut Line= 5
     2167638.894      242290.294     2167852.436      242088.472
     2167899.745      242032.048     2167997.401      241968.246
     2168324.224      241890.121
#Sta/Elev= 30
       0 2314.31    16.3 2313.65    88.2 2314.44   137.1 2311.06  260.932308.383
  290.392307.236  291.952307.057   309.8 2305.34   348.2 2304.46   354.6 2303.58
   425.8 2305.12     442 2306.56   448.5 2305.55   454.9  2302.4   458.2 2302.24
   467.9 2304.59   477.6 2305.45   481.72305.735  506.89 2305.96   513.5 2306.08
   523.3 2308.75   539.6 2306.23  552.312306.309  625.022307.467   660.3 2309.91
   666.8 2311.54   679.8 2312.75   722.3 2315.41   774.5 2326.62   820.1 2334.15
#Mann= 10 ,-1 , 0
       0     .06       0  260.93     .12       0  290.39     .06       0
  291.95     .07       0   448.5    .045       0   477.6     .07       0
   481.7     .06       0  506.89     .12       0  552.31     .06       0
  625.02     .12       0
#XS Ineff= 2 , 0
                          522.07         2308.84
Permanent Ineff=
       F       F
Bank Sta=448.5,477.6
XS Rating Curve= 0 ,0
Exp/Cntr=0.3,0.1

Type RM Length L Ch R = 1 ,26482   ,336.4,452.4,388.5
XS GIS Cut Line= 2
     2167669.824      242387.805      2168376.51      242036.005
#Sta/Elev= 30
       0 2319.92     6.6 2320.84   17.552320.435    55.7 2319.09   108.1 2315.88
   150.7 2315.38   199.8 2309.21  281.822306.081     321 2304.25   370.1 2304.27
   383.2 2303.21  393.982303.715   396.3 2303.49   399.6 2301.45   402.9 2300.66
   412.7 2299.88   419.3 2300.83   422.6 2302.73   425.8 2304.46   461.8    2304
  532.492305.269  538.182305.421   566.7 2305.93   582.92307.547   589.6 2307.96
   620.2 2312.85   671.5 2318.69   714.1 2321.34   766.5 2328.08   789.4 2331.93
#Mann= 10 ,-1 , 0
       0    .016       0   17.55     .06       0  281.82     .07       0
  393.98     .08       0   396.3    .045       0   422.6     .08       0
  532.49     .06       0  538.18     .12       0   582.9     .06       0
   620.2     .12       0
Bank Sta=396.3,422.6
XS Rating Curve= 0 ,0
Exp/Cntr=0.3,0.1

Type RM Length L Ch R = 1 ,26029.6 ,337.5,412.3,370.2
XS GIS Cut Line= 2
     2167730.676      242572.463     2168497.603      242309.442
#Sta/Elev= 30
       0 2321.81   33.642319.707   64.86 2319.14      85 2319.12    91.5 2317.99
  113.142317.882     255 2309.81   307.3 2303.22   336.7 2302.44   349.8 2299.31
   359.6 2300.26   405.4 2298.49  420.552298.534   431.5 2298.93   464.2 2298.85
   477.3 2302.34  502.042302.195  525.812302.187   542.7 2304.57   552.5    2307
   562.3 2307.05  584.92 2308.75   666.9 2314.39   693.1 2314.66  706.342315.528
     729  2317.8   758.5 2318.97   774.8  2320.7   787.9 2320.11   810.8 2325.47
#Mann= 11 ,-1 , 0
       0     .06       0   33.64     .12       0   64.86    .016       0
  113.14     .07       0  420.55     .08       0   431.5    .045       0
   464.2     .08       0  502.04     .06       0  525.81     .12       0
  584.92     .06       0  706.34     .12       0
#XS Ineff= 2 , 0
           336.7 2313.79  499.37         2314.02
Permanent Ineff=
       F       F
Bank Sta=431.5,464.2
XS Rating Curve= 0 ,0
Exp/Cntr=0.3,0.1

Type RM Length L Ch R = 1 ,25617.2 ,243.7,245.6,254.6
XS GIS Cut Line= 3
     2167932.468      242865.249     2168191.614      242688.349
     2168543.176      242362.828
#Sta/Elev= 30
       0 2333.02   29.622329.119    71.9 2324.03  101.382319.605     134 2315.22
  156.012314.328     170 2311.33  183.222311.047  255.62 2305.18   310.5 2302.87
   339.8 2300.97   344.4  2300.3   346.4  2299.8   349.6 2298.16   352.9 2297.41
   362.7 2298.07     379 2300.14   382.2 2300.49   411.6 2300.44   460.4 2302.51
     493 2302.96   528.9 2305.47   574.5  2306.9   594.1 2310.26   623.4 2317.64
   639.7 2320.31   659.3 2321.87   727.7 2329.97     757 2331.45   792.9 2335.42
#Mann= 8 ,-1 , 0
       0     .12       0   29.62     .06       0  101.38     .12       0
  156.01    .016       0  183.22     .06       0  255.62     .12       0
   344.4    .045       0     379     .12       0
Bank Sta=344.4,379
XS Rating Curve= 0 ,0
Exp/Cntr=0.3,0.1

Type RM Length L Ch R = 1 ,25371.6 ,264.6,275.4,264
XS GIS Cut Line= 3
     2168111.572      243022.181      2168406.31      242761.317
     2168707.518      242543.022
#Sta/Elev= 30
       0 2321.03   12.572320.552    39.4 2319.21    62.3 2317.57    78.7 2315.56
  125.452312.596   144.3 2311.83  158.052310.358  194.022307.837   242.7  2304.7
   308.3 2302.36  340.472299.195   357.5 2298.88   383.8    2300   386.1 2299.17
   393.6 2296.34   400.1 2296.49   409.9 2299.05     4192300.635   455.6 2299.26
  470.252299.495   511.1 2301.92   520.9 2303.85   533.9 2304.32     547 2309.94
   654.6 2339.48   693.8 2348.85   726.4  2357.8     746 2362.12   765.6 2364.85
#Mann= 10 ,-1 , 0
       0     .12       0   12.57     .06       0  125.45     .12       0
  158.05    .016       0  194.02     .06       0  340.47     .12       0
   386.1    .045       0   409.9     .12       0     419     .06       0
  470.25     .12       0
Bank Sta=386.1,409.9
XS Rating Curve= 0 ,0
Exp/Cntr=0.3,0.1

Type RM Length L Ch R = 1 ,25096.2 ,223.3,224.6,229.8
XS GIS Cut Line= 2
     2168235.751      243155.313     2168838.749      242696.161
#Sta/Elev= 30
       0 2319.87      49 2317.93   82.492315.325   157.72312.915   176.4 2311.86
  197.622312.089  221.862311.549  279.652310.142   316.9  2308.5   333.2  2305.3
   346.3 2297.87   352.8 2295.67   356.1 2295.61   365.9 2295.75   375.7 2297.98
     392 2300.24   424.7 2301.58   434.5 2303.56   447.6 2304.34   460.6 2306.39
   493.3 2313.74   506.4 2315.32     539 2316.63   571.7 2313.51   601.1 2322.42
   666.4 2335.36   692.6 2339.55   728.5 2339.42   744.8  2335.5   757.9 2336.75
#Mann= 8 ,-1 , 0
       0     .06       0   82.49     .12       0   157.7    .016       0
  197.62     .12       0  221.86     .06       0  279.65     .12       0
   346.3    .045       0   375.7     .12       0
Bank Sta=346.3,375.7
XS Rating Curve= 0 ,0
Exp/Cntr=0.3,0.1

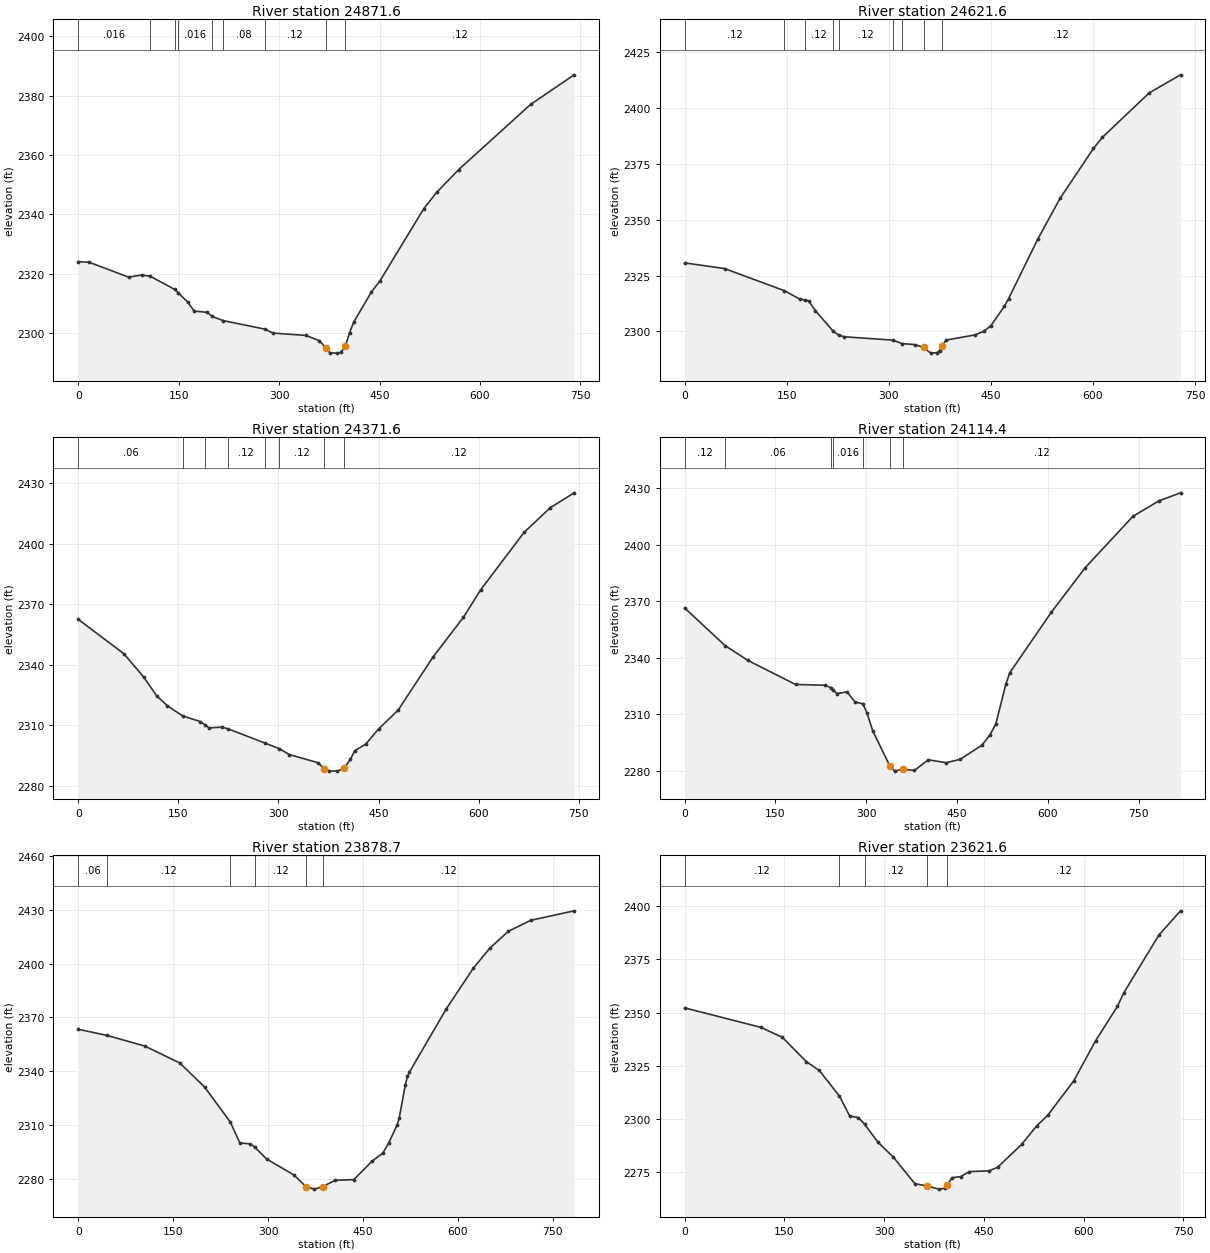
Type RM Length L Ch R = 1 ,24871.6 ,235.1,250,264.9
XS GIS Cut Line= 3
     2168383.691       243299.67     2168692.059      243079.049
     2168973.629      242852.657
#Sta/Elev= 30
       0 2324.11    16.3  2323.9    75.2 2318.89    94.8 2319.61  107.752319.165
  144.072314.754  149.262313.635   163.4  2310.5   173.2 2307.44   192.8 2307.03
  200.012305.636  216.712304.229  279.082301.351   290.9 2300.04   339.9 2299.24
   359.6 2297.52   369.4 2295.17   375.9 2293.38   385.7 2293.28   392.2 2293.53
   398.7 2295.53   405.2 2300.15   411.7 2303.85   437.8 2313.88   450.8  2317.7
   515.9 2341.92   535.4  2347.5     568 2355.09   675.4 2377.07   740.5 2387.07
#Mann= 9 ,-1 , 0
       0    .016       0  107.75     .12       0  144.07     .06       0
  149.26    .016       0  200.01     .12       0  216.71     .08       0
  279.08     .12       0   369.4    .045       0   398.7     .12       0
Bank Sta=369.4,398.7
XS Rating Curve= 0 ,0
Exp/Cntr=0.3,0.1

Type RM Length L Ch R = 1 ,24621.6 ,251.8,250,245.4
XS GIS Cut Line= 3
     2168417.082      243396.162     2168772.391      243314.091
     2169121.924      243212.911
#Sta/Elev= 30
       0 2330.67    58.6 2328.13   146.62318.199   169.3 2314.44  176.92 2314.01
   182.3 2313.62   192.1 2309.25  218.322300.065  226.092298.334   234.4 2297.56
  306.182296.051  319.222294.518   338.6 2294.03   351.6 2292.76   361.4 2290.23
   371.2 2290.49   374.5 2291.34   377.8 2293.35   384.3 2296.08     427 2298.41
   440.1 2300.13   449.9 2302.52   469.6 2311.14   476.1  2314.7   518.7 2341.22
   551.5 2359.52   600.7 2381.96   613.8 2386.92   682.6 2406.84   728.6 2414.93
#Mann= 9 ,-1 , 0
       0     .12       0   146.6    .016       0  176.92     .12       0
  218.32     .06       0  226.09     .12       0  306.18     .06       0
  319.22     .12       0   351.6    .045       0   377.8     .12       0
Bank Sta=351.6,377.8
XS Rating Curve= 0 ,0
Exp/Cntr=0.3,0.1

Type RM Length L Ch R = 1 ,24371.6 ,261.3,257.2,256.9
XS GIS Cut Line= 3
     2168473.208      243648.435     2168840.769       243545.74
     2169175.321      243409.614
#Sta/Elev= 30
       0 2362.43    68.5 2345.35    97.9  2333.9   117.4 2324.55   133.7 2319.56
  156.462314.565   182.7 2311.77  189.262310.264   195.7 2308.61   215.3 2308.99
  224.512308.141  279.062301.177  300.832298.362   316.4 2295.37   358.8  2291.4
   368.6 2288.48   375.1  2287.3   388.1 2287.18   397.9 2288.57   407.7 2292.99
   414.2  2297.3   430.4 2300.48     450 2308.12   479.2  2317.4   531.3 2343.68
   576.9 2363.38   602.9 2377.08     668 2405.57     707 2417.72   742.8 2425.14
#Mann= 8 ,-1 , 0
       0     .06       0  156.46     .12       0  189.26    .016       0
  224.51     .12       0  279.06     .06       0  300.83     .12       0
   368.6    .045       0   397.9     .12       0
Bank Sta=368.6,397.9
XS Rating Curve= 0 ,0
Exp/Cntr=0.3,0.1

Type RM Length L Ch R = 1 ,24114.4 ,279.5,235.7,191.7
XS GIS Cut Line= 3
     2168543.645      243930.602     2168915.572       243776.89
     2169197.093      243469.885
#Sta/Elev= 30
       0 2366.37   66.912346.371   104.7 2338.49   183.2 2325.76   232.3 2325.37
  242.362323.898  245.482322.674   251.9 2320.95   268.3  2321.8   281.4 2316.44
  294.422315.523     301 2310.86   310.8 2301.07   338.8 2282.59   346.8 2279.77
   359.9  2280.8   379.5 2280.12   402.4 2285.78     432 2284.25   454.9 2286.01
     491 2293.53   504.1 2298.92     514 2304.82   530.4 2325.79   536.9 2331.94
   605.8 2364.15   661.6 2387.74   740.3 2414.94   782.9 2423.15     819 2427.47
#Mann= 7 ,-1 , 0
       0     .12       0   66.91     .06       0  242.36     .12       0
  245.48    .016       0  294.42     .12       0   338.8    .045       0
   359.9     .12       0
Bank Sta=338.8,359.9
XS Rating Curve= 0 ,0
Exp/Cntr=0.3,0.1

Type RM Length L Ch R = 1 ,23878.7 ,239,257.2,276.3
XS GIS Cut Line= 3
     2169057.134      244230.676     2169065.312       243801.63
     2169248.852      243498.212
#Sta/Elev= 30
       0 2363.43   45.052360.032   104.8 2354.12   160.5 2344.64   199.8 2331.19
   240.42311.672   255.5 2300.04   271.9 2299.51  279.292297.587   298.1 2291.03
   340.7 2282.24   360.3 2275.56   373.4 2274.29   386.5 2275.75   406.2 2279.22
   435.6  2279.6   464.9 2290.05   481.2  2294.3   490.9 2300.11     504 2310.06
   507.2 2313.75     517 2332.45   520.2 2337.09   523.5 2339.57     582 2374.99
   624.3  2397.4   650.4 2408.59   679.6 2417.99   715.4 2424.19   783.7 2429.46
#Mann= 6 ,-1 , 0
       0     .06       0   45.05     .12       0   240.4    .016       0
  279.29     .12       0   360.3    .045       0   386.5     .12       0
Bank Sta=360.3,386.5
XS Rating Curve= 0 ,0
Exp/Cntr=0.3,0.1

Type RM Length L Ch R = 1 ,23621.6 ,263.8,250,233
XS GIS Cut Line= 3
     2169123.335      244254.055     2169292.117      243922.114
     2169486.397      243603.205
#Sta/Elev= 30
       0 2352.24   114.3  2343.1     147 2338.37   182.9 2326.99   202.5 2322.78
  232.862310.747   248.3 2301.33   261.3 2300.65  270.692297.485   290.7 2289.05
   313.6 2282.12   346.3 2269.53   364.9 2268.45   382.2 2266.96     392 2267.35
   395.3 2268.83   401.9 2272.32     415 2272.84   428.1  2275.2   457.6 2275.57
   470.7 2277.23   506.7 2287.98   529.6 2296.74     546 2301.67   585.3 2317.94
   618.1 2336.78   650.8 2352.89   660.6 2359.37   713.1 2386.42   745.8 2397.89
#Mann= 5 ,-1 , 0
       0     .12       0  232.86    .016       0  270.69     .12       0
   364.9    .045       0   395.3     .12       0
Bank Sta=364.9,395.3
XS Rating Curve= 0 ,0
Exp/Cntr=0.3,0.1

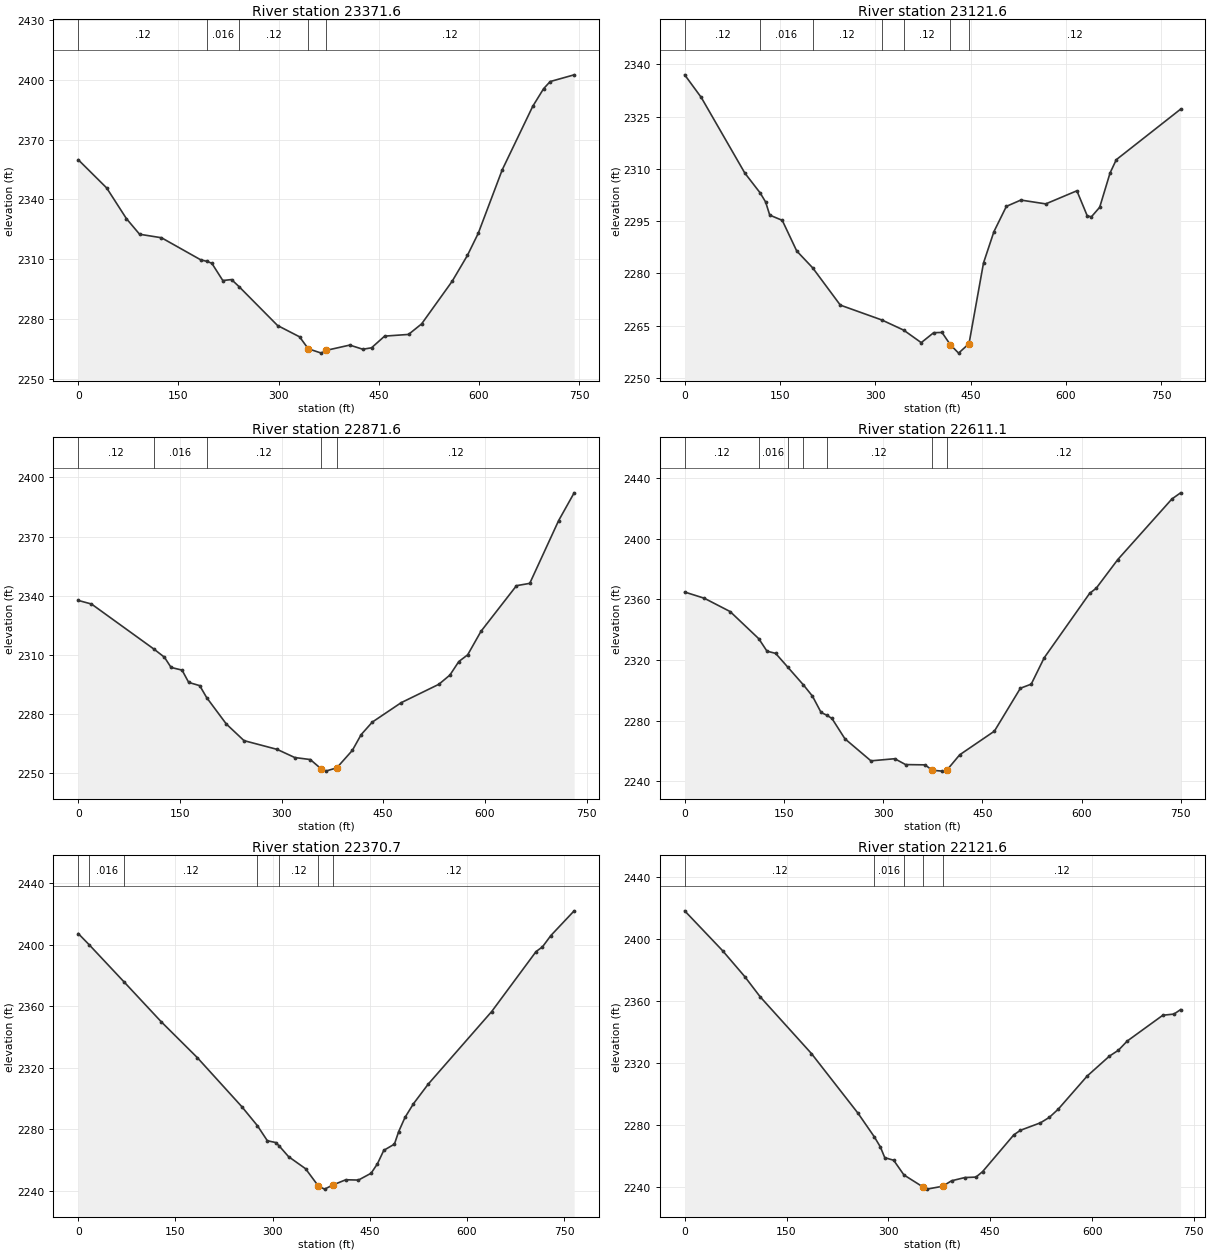
Type RM Length L Ch R = 1 ,23371.6 ,240.1,250,258.3
XS GIS Cut Line= 3
     2169484.084      244364.358     2169521.218      244005.401
     2169555.325       243625.21
#Sta/Elev= 30
       0 2359.88    42.6 2345.74    72.2 2330.34    91.9 2322.53   124.7 2320.77
   183.7 2309.66  193.142308.911   200.1 2307.97   216.5 2299.34   229.6 2299.82
  241.132296.186   298.5  2276.8   331.4 2271.14   344.5 2265.14   364.1 2262.96
   370.7 2264.29   406.6 2266.99   426.1 2264.91   439.2 2265.63   458.8 2271.48
   494.6 2272.33   514.2 2277.61   559.9 2298.95   582.7 2311.88     599    2323
   634.9 2354.81   680.6 2386.64   696.9 2395.49   706.7 2399.04   742.6 2402.41
#Mann= 5 ,-1 , 0
       0     .12       0  193.14    .016       0  241.13     .12       0
   344.5    .045       0   370.7     .12       0
Bank Sta=344.5,370.7
XS Rating Curve= 0 ,0
Exp/Cntr=0.3,0.1

Type RM Length L Ch R = 1 ,23121.6 ,233.9,250,273.2
XS GIS Cut Line= 3
     2169613.226       244370.49     2169764.943      243970.317
     2169871.886      243634.209
#Sta/Elev= 30
       0    2337    26.1 2330.51    94.7  2308.8  118.772303.125   127.4 2300.51
   133.9 2296.74   153.6 2295.24   176.4 2286.44  201.512281.604     245 2270.91
   310.52266.633  344.752263.729   372.4 2260.14     392    2263   405.1 2263.06
   418.2 2259.54   431.2 2257.13   447.6 2259.85   470.4    2283   486.8 2291.99
   506.4 2299.25   529.2 2301.06   568.4 2299.96   617.4 2303.72   633.7 2296.54
   640.2 2296.24   653.3 2298.99   669.6 2308.82   679.4 2312.64   780.7 2327.15
#Mann= 7 ,-1 , 0
       0     .12       0  118.77    .016       0  201.51     .12       0
   310.5    .016       0  344.75     .12       0   418.2    .045       0
   447.6     .12       0
Bank Sta=418.2,447.6
XS Rating Curve= 0 ,0
Exp/Cntr=0.3,0.1

Type RM Length L Ch R = 1 ,22871.6 ,246.1,260.4,268.6
XS GIS Cut Line= 3
     2169663.672      244414.948     2169921.593      244151.825
     2170214.002      243936.368
#Sta/Elev= 30
       0 2337.67    19.6 2335.84  112.042312.925   127.2 2308.88     137 2303.71
   153.2 2302.34     163 2296.12   179.3 2294.47  189.472288.439   218.5 2275.04
   244.6 2266.61   293.5 2262.17   319.5 2258.04   342.4 2257.02   358.7 2252.23
   365.2 2251.15   381.5 2252.82   404.4 2261.64   417.5 2269.68   433.9    2276
   476.4 2285.82   532.1 2295.16   548.4 2299.84   561.5 2306.68   574.6 2310.09
   594.2 2321.99   646.6 2345.14   666.2 2346.32   708.8 2378.13   731.7  2392.2
#Mann= 5 ,-1 , 0
       0     .12       0  112.04    .016       0  189.47     .12       0
   358.7    .045       0   381.5     .12       0
Bank Sta=358.7,381.5
XS Rating Curve= 0 ,0
Exp/Cntr=0.3,0.1

Type RM Length L Ch R = 1 ,22611.1 ,258.2,240.5,230.3
XS GIS Cut Line= 2
     2169730.676      244511.265     2170415.572      244206.578
#Sta/Elev= 30
       0 2364.84    29.5 2360.78    68.7 2351.97  112.012334.055   124.4 2325.86
   137.5 2324.39  156.092315.196  179.592303.543   193.1 2296.23   206.2 2285.42
   214.42283.725   222.6 2281.48   242.2 2268.08   281.5 2253.54   317.5 2254.94
   333.9 2251.08   363.4 2250.89   374.1 2247.34   389.5 2246.76   396.1 2247.33
   415.7 2257.53   468.1  2273.1   507.4 2301.41   523.8 2304.11   543.4 2321.49
   612.1 2363.97     622 2367.34   654.7 2386.29   736.5 2426.23   749.6 2430.25
#Mann= 7 ,-1 , 0
       0     .12       0  112.01    .016       0  156.09     .12       0
  179.59    .016       0   214.4     .12       0   374.1    .045       0
   396.1     .12       0
Bank Sta=374.1,396.1
XS Rating Curve= 0 ,0
Exp/Cntr=0.3,0.1

Type RM Length L Ch R = 1 ,22370.7 ,252.6,249.1,240
XS GIS Cut Line= 3
     2169944.218      244922.724     2170100.468      244601.109
     2170422.083      244349.807
#Sta/Elev= 30
       0 2407.23   17.132399.841   70.382375.936   127.9 2349.95   183.7 2326.58
   252.6  2294.6  276.762282.177     292 2272.45   305.1 2271.25  310.432268.986
   324.8 2262.08     351 2254.25   370.9 2242.91   380.4 2240.96   393.5  2243.7
   413.1 2247.05   432.7 2246.86   452.2  2251.3     462 2257.45   471.8  2266.2
   488.2 2270.23   494.7  2278.3   504.5 2287.57   517.6 2296.51   540.4 2309.27
   638.4 2356.49   706.9  2395.5   716.7 2398.52   729.8 2405.94   765.7 2421.99
#Mann= 7 ,-1 , 0
       0     .12       0   17.13    .016       0   70.38     .12       0
  276.76    .016       0  310.43     .12       0   370.9    .045       0
   393.5     .12       0
Bank Sta=370.9,393.5
XS Rating Curve= 0 ,0
Exp/Cntr=0.3,0.1

Type RM Length L Ch R = 1 ,22121.6 ,260.3,250,238.5
XS GIS Cut Line= 3
     2170083.596      245070.808     2170285.223      244768.366
     2170511.994      244479.948
#Sta/Elev= 30
       0 2418.33    55.7 2392.62    88.4 2375.85   111.3 2362.68   186.7 2326.04
   255.4 2287.38  279.462272.071   288.2 2265.65   294.7  2258.7   307.8 2257.05
  322.932247.527   350.4 2239.93   356.9 2238.37   379.9 2240.23     393 2243.76
   412.6 2245.86     429 2246.15   438.8 2249.71   484.7 2273.45   494.5 2276.42
     524 2281.26   537.1 2284.78   550.2 2290.09   592.8  2311.5   625.6  2324.4
   638.7 2328.15   651.8 2334.14   704.2 2350.81   720.6 2351.57   730.4 2354.47
#Mann= 5 ,-1 , 0
       0     .12       0  279.46    .016       0  322.93     .12       0
   350.4    .045       0   379.9     .12       0
Bank Sta=350.4,379.9
XS Rating Curve= 0 ,0
Exp/Cntr=0.3,0.1