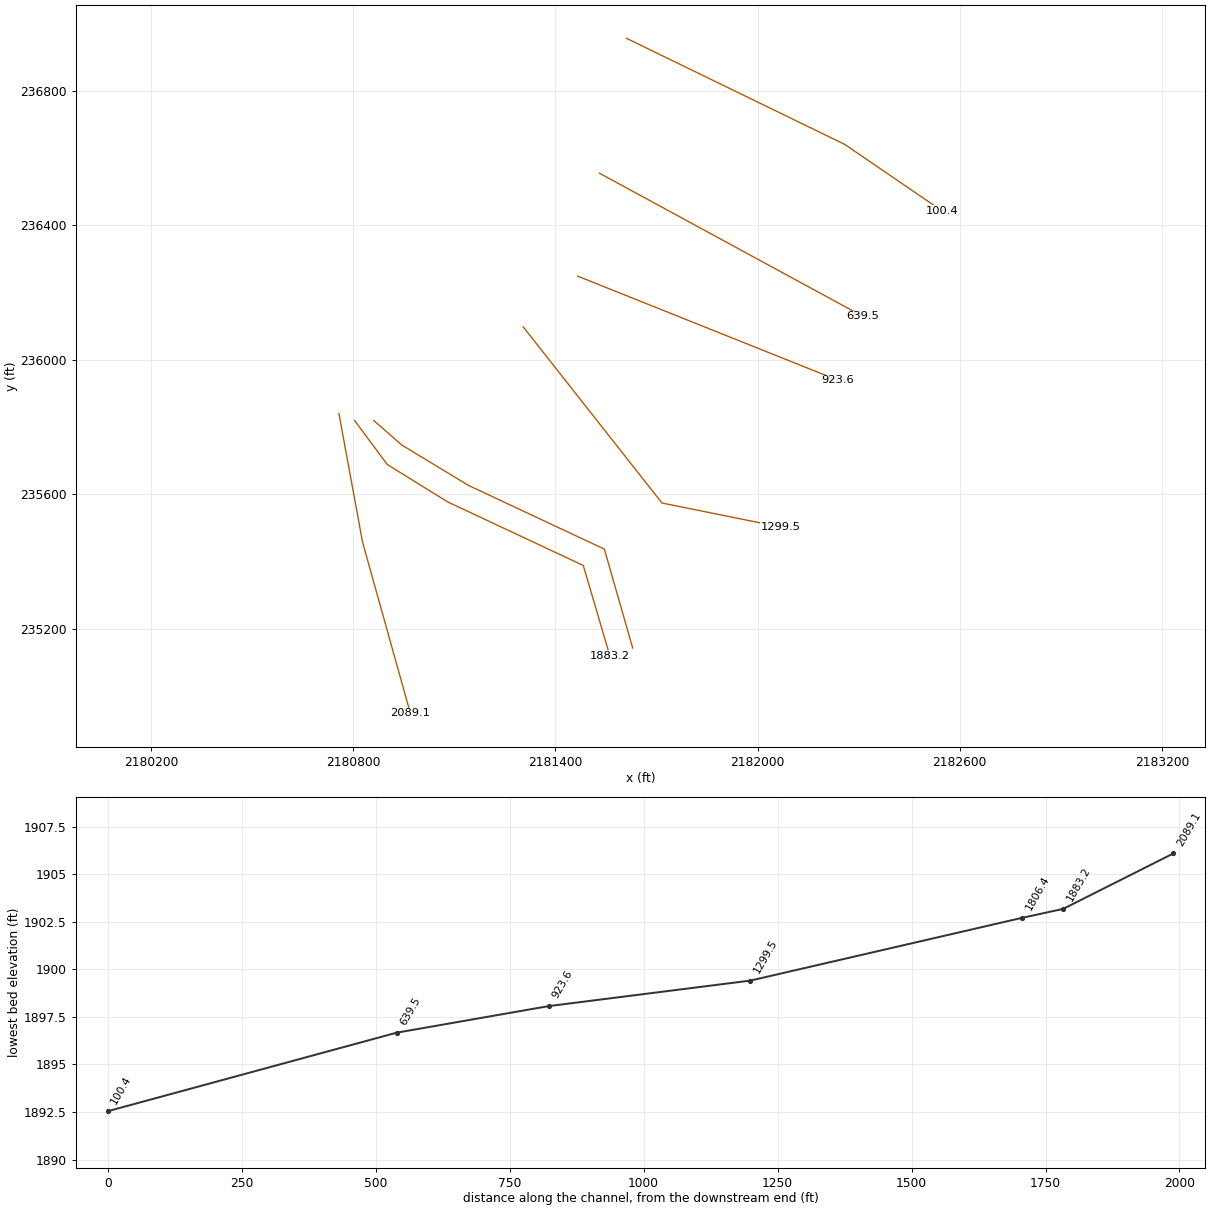
HEC-RAS study COVECK.prj: COVECK

--- COVECK.g01 (geometry) --- (continued)

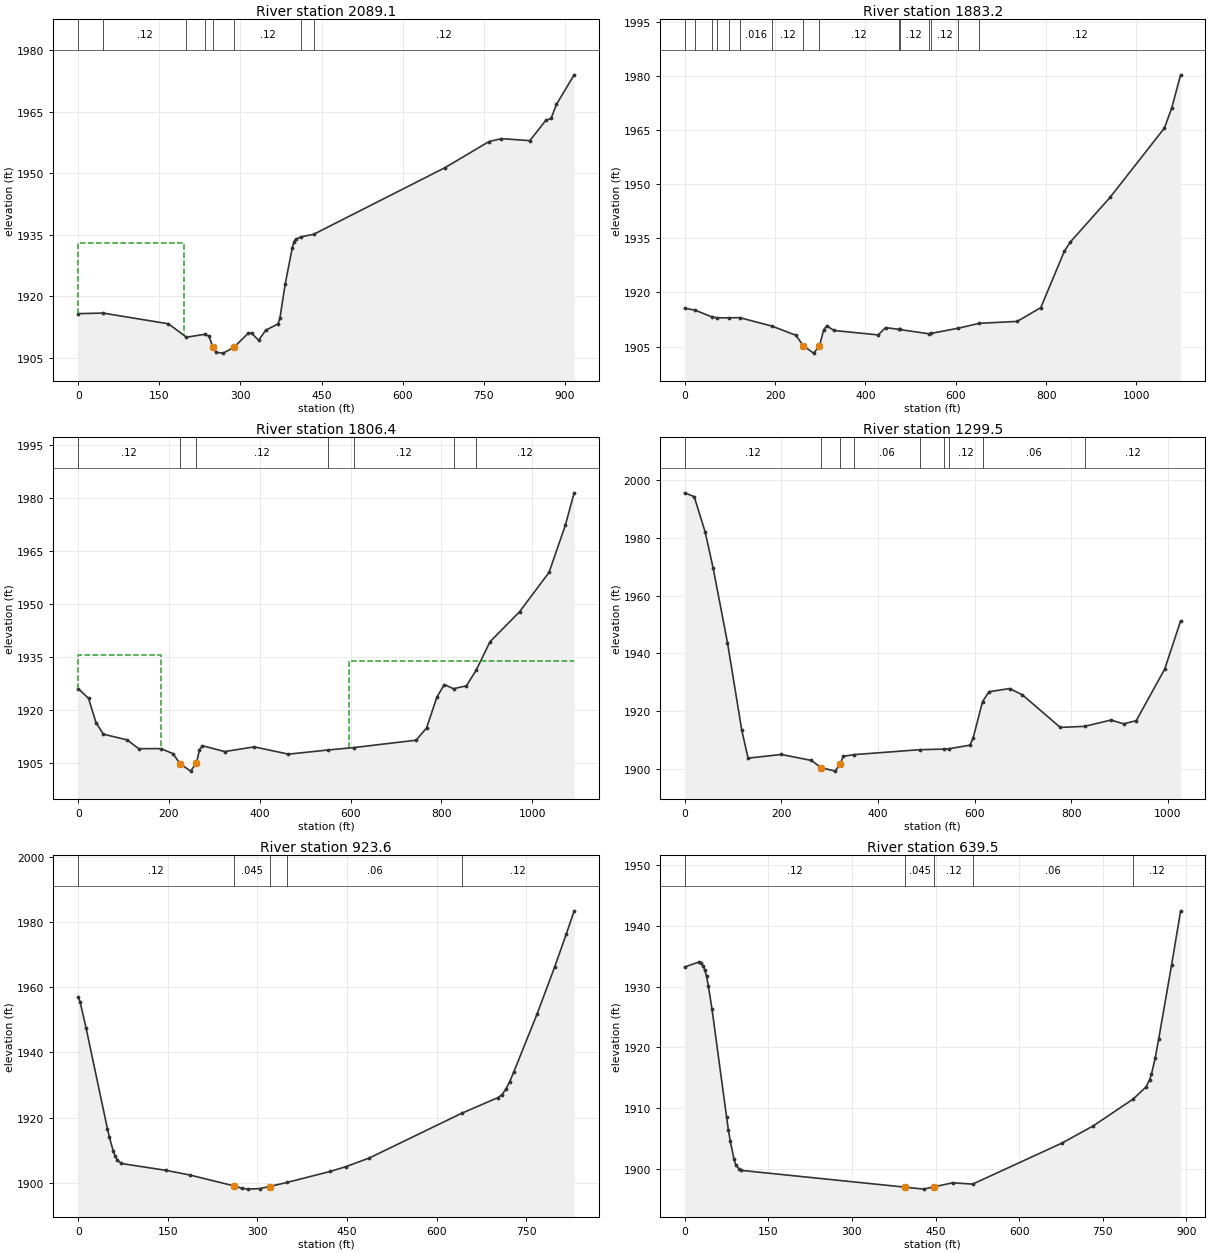
Type RM Length L Ch R = 1 ,2089.1  ,173.1,205.9,238.2
XS GIS Cut Line= 3
      2180758.02      235840.258     2180828.333      235457.446
     2180970.057      234949.149
#Sta/Elev= 30
       0 1915.74   45.881915.879   166.8 1913.26  200.121909.987  233.971910.696
     242 1910.26   248.6 1907.59   255.1 1906.27   268.2  1906.1   287.8 1907.52
     314 1910.92   320.5 1910.99   333.6 1909.23   346.7  1911.7   369.6 1913.25
   372.9 1914.65   382.7 1922.98   395.8 1931.84     399 1933.34   402.3 1933.92
  411.731934.492  435.011935.096   677.6 1951.35   759.6 1957.76   782.5 1958.47
     835 1957.98   864.5 1962.94   874.3 1963.41   884.1 1966.82   916.9 1974.05
#Mann= 8 ,-1 , 0
       0     .06       0   45.88     .12       0  200.12    .016       0
  233.97     .12       0   248.6    .045       0   287.8     .12       0
  411.73     .06       0  435.01     .12       0
#XS Ineff= 2 , 0
          195.46 1932.96
Permanent Ineff=
       F       F
Bank Sta=248.6,287.8
XS Rating Curve= 0 ,0
Exp/Cntr=0.3,0.1

Type RM Length L Ch R = 1 ,1883.2  ,77.8,76.8,76.3
XS GIS Cut Line= 5
     2180804.895      235819.425     2180901.249      235689.217
     2181080.242      235578.106      2181483.02      235388.869
     2181561.854      235120.156
#Sta/Elev= 30
       0  1915.6   22.761915.079    60.71913.196   72.421912.966   97.441912.951
  122.081912.998  193.141910.663   246.2 1908.12   262.5 1905.23   285.2 1903.18
   298.1  1905.1   307.8 1909.65   314.3 1910.75   330.5 1909.45   428.3 1908.22
   444.6 1910.24  474.721909.756  475.521909.724  540.311908.537  544.961908.636
  605.581910.076  652.071911.439   735.9 1911.96   788.2 1915.78   840.5 1931.45
   853.5 1933.93   941.4 1946.29  1061.9 1965.51  1078.2 1971.13  1097.7 1980.24
#Mann= 15 ,-1 , 0
       0     .12       0   22.76    .016       0    60.7     .06       0
   72.42    .016       0   97.44     .06       0  122.08    .016       0
  193.14     .12       0   262.5    .045       0   298.1     .12       0
  474.72    .016       0  475.52     .12       0  540.31    .016       0
  544.96     .12       0  605.58    .016       0  652.07     .12       0
Bank Sta=262.5,298.1
XS Rating Curve= 0 ,0
Exp/Cntr=0.3,0.1

Type RM Length L Ch R = 1 ,1806.4  ,520.2,506.9,493
XS GIS Cut Line= 5
     2180861.608      235819.656     2180944.941       235746.74
     2181142.742      235626.717      2181545.52      235437.481
     2181629.562      235143.593
#Sta/Elev= 30
       0  1926.1    22.8 1923.33    39.1 1916.48    55.4 1913.19   107.5 1911.56
   133.5 1909.07   182.4 1909.09   208.5 1907.67   224.8 1904.79   247.6 1902.71
   260.6 1905.02   267.2 1908.75   273.7 1909.91   322.6 1908.25   387.9 1909.59
   463.2 1907.52  549.55 1908.69  607.26 1909.38   744.6 1911.48   767.5 1914.93
   790.4 1923.68   806.6 1927.25  826.961926.061   855.4 1926.89  876.79 1931.28
   907.4 1939.37   972.5 1947.87  1037.5 1959.03  1073.3 1972.36  1092.8 1981.57
#Mann= 7 ,-1 , 0
       0     .12       0   224.8    .045       0   260.6     .12       0
  549.55    .016       0  607.26     .12       0  826.96    .016       0
  876.79     .12       0
#XS Ineff= 2 , 0
           183.1 1935.59  597.73          1933.8
Permanent Ineff=
       F       F
Bank Sta=224.8,260.6
XS Rating Curve= 0 ,0
Exp/Cntr=0.3,0.1

Type RM Length L Ch R = 1 ,1299.5  ,356.2,375.9,395.6
XS GIS Cut Line= 3
     2181304.895      236098.071     2181716.353      235574.633
     2182069.666      235502.968
#Sta/Elev= 30
       0 1995.43    19.7 1994.11    42.6 1981.81      59 1969.37    88.6 1943.72
   118.1 1913.56   131.2 1903.88   200.1 1905.16   262.4 1903.09   282.1 1900.62
   311.6 1899.41   321.4 1901.79     328 1904.49  350.241905.099  487.291906.813
  535.971907.007  546.62 1907.13   590.4 1908.37   596.9 1910.82  616.331923.357
   629.7  1926.8   672.4  1927.9   698.6 1925.77   777.2  1914.5  827.591914.859
   882.1 1917.03   908.3 1915.73   934.5 1916.83   993.5 1934.67  1026.3 1951.26
#Mann= 9 ,-1 , 0
       0     .12       0   282.1    .045       0   321.4     .12       0
  350.24     .06       0  487.29    .016       0  535.97     .06       0
  546.62     .12       0  616.33     .06       0  827.59     .12       0
Bank Sta=282.1,321.4
XS Rating Curve= 0 ,0
Exp/Cntr=0.3,0.1

Type RM Length L Ch R = 1 ,923.6   ,288.7,284.1,278.8
XS GIS Cut Line= 2
     2181466.368      236249.062     2182237.201      235940.034
#Sta/Elev= 30
       0 1956.98     3.3 1955.34    13.1 1947.52      49 1916.52    52.3 1913.93
    58.8 1909.65    62.1 1908.09    65.4  1907.1    71.9 1905.93   147.1 1903.82
   186.4 1902.42   261.6 1899.03   274.6 1898.31   284.4 1898.07   304.1 1898.24
   320.4 1898.87  349.341900.103   421.8 1903.48   447.9 1904.94   487.2 1907.59
  642.431921.348     703 1926.12   709.5 1927.03     716 1928.64   722.6 1931.03
   729.1 1933.85   768.4 1951.74   797.8 1966.14   817.4 1976.29   830.5 1983.37
#Mann= 5 ,-1 , 0
       0     .12       0   261.6    .045       0   320.4     .12       0
  349.34     .06       0  642.43     .12       0
Bank Sta=261.6,320.4
XS Rating Curve= 0 ,0
Exp/Cntr=0.3,0.1

Type RM Length L Ch R = 1 ,639.5   ,537.1,539.1,538.9
XS GIS Cut Line= 2
     2181531.038      236555.051     2182312.288      236129.704
#Sta/Elev= 30
       0 1933.26    26.2  1934.1    29.4 1933.97    32.7  1933.5      36 1932.78
    39.2 1931.74    42.5  1930.1    49.1 1926.28    75.2 1908.51    78.5 1906.36
    81.8 1904.56    88.3 1901.68    91.6 1900.64    98.1 1899.94   101.4 1899.76
   395.7 1896.99   428.4 1896.67     448 1897.07   480.7 1897.71  516.561897.498
     677 1904.27   732.6 1907.08  803.941911.479   827.4 1913.48   833.9 1914.71
   837.2 1915.61   843.8 1918.21   850.3 1921.46   873.2 1933.54   889.5 1942.51
#Mann= 5 ,-1 , 0
       0     .12       0   395.7    .045       0     448     .12       0
  516.56     .06       0  803.94     .12       0
Bank Sta=395.7,448
XS Rating Curve= 0 ,0
Exp/Cntr=0.3,0.1

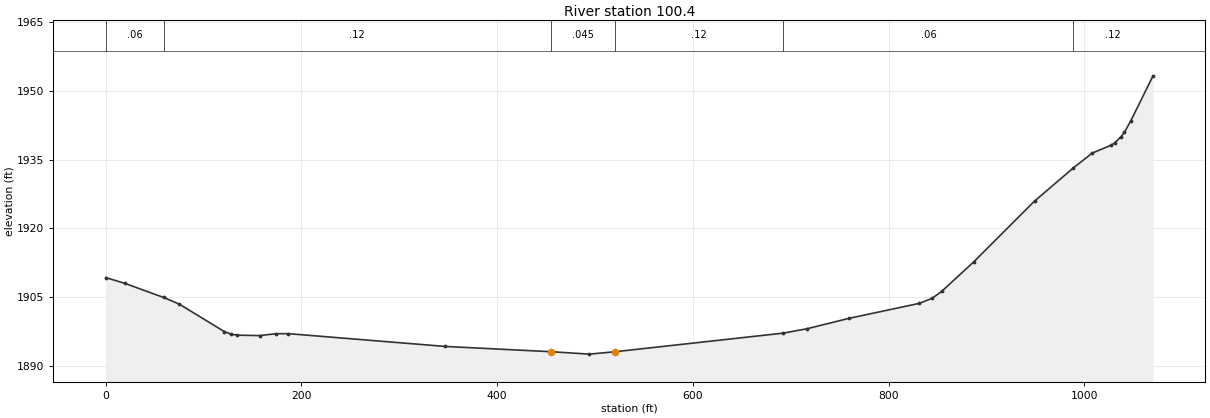
Type RM Length L Ch R = 1 ,100.4   ,82.9,100.4,117.6
XS GIS Cut Line= 3
     2181611.333      236956.093     2182258.635      236640.772
     2182547.697      236442.855
#Sta/Elev= 30
       0 1909.26    19.6 1907.98    59.11904.916    75.3 1903.44   121.1 1897.47
   127.6 1896.93   134.2 1896.68   157.1 1896.59   173.5 1896.99   186.6 1897.01
   346.9 1894.22   454.9 1893.07   494.2 1892.54   520.4 1893.06  692.451897.128
   716.8 1898.09   759.3 1900.34   831.3 1903.62   844.4 1904.71   854.3 1906.24
     887 1912.68   949.2 1925.96   988.91933.207  1008.1 1936.43  1027.8  1938.2
  1031.1 1938.66  1037.6 1940.02  1040.9 1940.94  1047.4 1943.42  1070.3 1953.31
#Mann= 6 ,-1 , 0
       0     .06       0    59.1     .12       0   454.9    .045       0
   520.4     .12       0  692.45     .06       0   988.9     .12       0
Bank Sta=454.9,520.4
XS Rating Curve= 0 ,0
Exp/Cntr=0.3,0.1

Chan Stop Cuts=-1
Use User Specified Reach Order=0
Composite Channel Slope=5